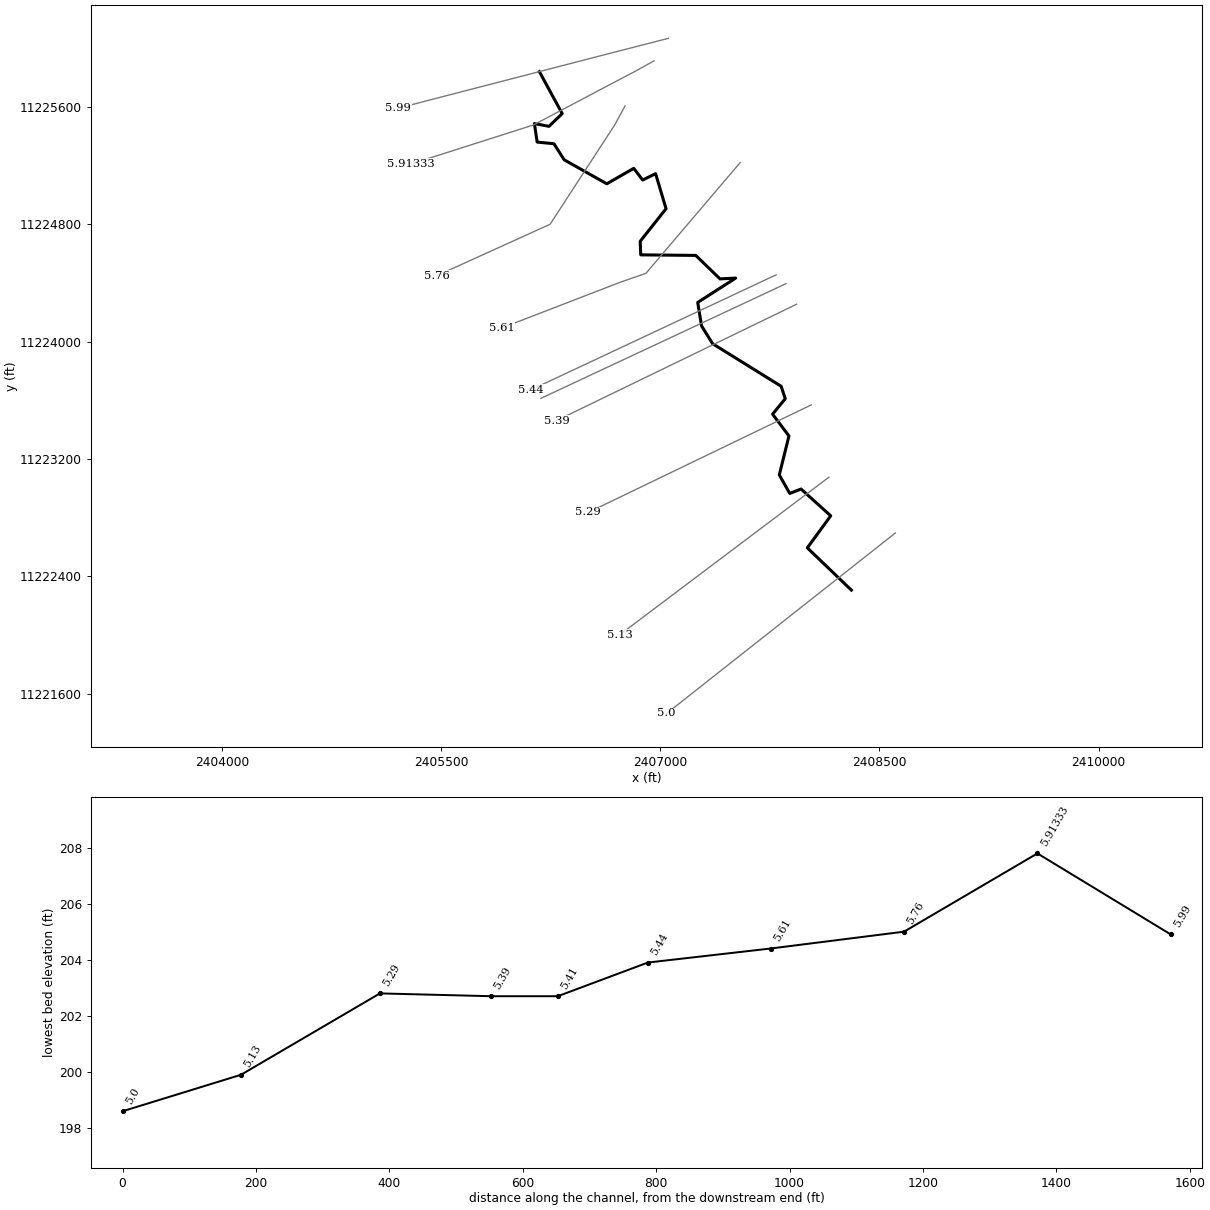
--- BeaverSA.prj (project) ---

Proj Title=Beaver Cr. - SA and SA Connection
Current Plan=p01
Default Exp/Contr=0.3,0.1
English Units
Geom File=g01
Unsteady File=u01
Plan File=p01
Y Axis Title=Elevation
X Axis Title(PF)=Main Channel Distance
X Axis Title(XS)=Station
BEGIN DESCRIPTION:
END DESCRIPTION:
DSS Start Date=5/22/1974
DSS Start Time=0000
DSS End Date=5/25/1974
DSS End Time=2400
DSS File=dss
DSS Export Rating Curves= 0
DSS Export Rating Curve Sorted= 0
DSS Export Volume Flow Curves= 0
DXF OffsetX= 0
DXF OffsetY= 0
DXF ScaleX= 1
DXF ScaleY= 10

--- BeaverSA.p01 (plan) ---

Plan Title=Existing Conditions
Program Version=3.11
Short Identifier=Exist Cond
Simulation Date=5/22/1974,0000,5/25/1974,2400
Geom File=g01
Flow File=u01
Subcritical Flow
K Sum by GR= 0
Std Step Tol= 0.01
Critical Tol= 0.01
Num of Std Step Trials= 20
Max Error Tol= 0.33
Flow Tol Ratio= 0.001
Split Flow NTrial= 30
Split Flow Tol= 0.02
Split Flow Ratio= 0.02
Log Output Level= 0
Friction Slope Method= 1
Unsteady Friction Slope Method= 2
Calc Critical at every XS
Parabolic Critical Depth
Global Vel Dist= 10 , 10 , 10
Global Log Level= 0
CheckData=True
Encroach Param=-1 ,0,0, 0
BEGIN DESCRIPTION:
Exiting conditions for the Beaver Creek overcrossing
END DESCRIPTION:
Computation Interval=1MIN
Output Interval=1HOUR
Run HTab= 1
Run UNet= 1
Run PostProcess= 1
UNET Theta= 0.8
UNET Theta Warmup= 1
UNET ZTol= 0.01
UNET ZSATol= 0.1
UNET MxIter= 20
UNET MaxInSteps= 20
UNET DtIC= 0
UNET DtMin= 0
UNET MaxCRTS= 20
UNET WFStab= 1
UNET SFStab= 1
UNET WFX= 1
UNET SFX= 1
UNET DSS MLevel= 4
UNET Convert EG Bridges= 1
UNET Use Existing IB Tables=-1
UNET Froude Reduction=False
UNET Froude Limit= 1
UNET Froude Power= 10
Instantaneous Interval=2HOUR
DSS File=dss
Write IC File= 0
IC Time=10,,
Echo Input=False
Echo Output=False
Write Detailed= 0
Stage Flow Hydrograph=Beaver Creek    ,Kentwood        ,5.99
Stage Flow Hydrograph=Beaver Creek    ,Kentwood        ,5.95166*
Stage Flow Hydrograph=Beaver Creek    ,Kentwood        ,5.91333*
Stage Flow Hydrograph=Beaver Creek    ,Kentwood        ,5.875*
Stage Flow Hydrograph=Beaver Creek    ,Kentwood        ,5.83666*
Stage Flow Hydrograph=Beaver Creek    ,Kentwood        ,5.79833*
Stage Flow Hydrograph=Beaver Creek    ,Kentwood        ,5.76
Stage Flow Hydrograph=Beaver Creek    ,Kentwood        ,5.7225*
Stage Flow Hydrograph=Beaver Creek    ,Kentwood        ,5.685*
Stage Flow Hydrograph=Beaver Creek    ,Kentwood        ,5.6475*
Stage Flow Hydrograph=Beaver Creek    ,Kentwood        ,5.61
Stage Flow Hydrograph=Beaver Creek    ,Kentwood        ,5.576*
Stage Flow Hydrograph=Beaver Creek    ,Kentwood        ,5.542*
Stage Flow Hydrograph=Beaver Creek    ,Kentwood        ,5.508*
Stage Flow Hydrograph=Beaver Creek    ,Kentwood        ,5.474*
Stage Flow Hydrograph=Beaver Creek    ,Kentwood        ,5.44
Stage Flow Hydrograph=Beaver Creek    ,Kentwood        ,5.425*
Stage Flow Hydrograph=Beaver Creek    ,Kentwood        ,5.41
Stage Flow Hydrograph=Beaver Creek    ,Kentwood        ,5.39
Stage Flow Hydrograph=Beaver Creek    ,Kentwood        ,5.35666*
Stage Flow Hydrograph=Beaver Creek    ,Kentwood        ,5.32333*
Stage Flow Hydrograph=Beaver Creek    ,Kentwood        ,5.29
Stage Flow Hydrograph=Beaver Creek    ,Kentwood        ,5.25*
Stage Flow Hydrograph=Beaver Creek    ,Kentwood        ,5.21*
Stage Flow Hydrograph=Beaver Creek    ,Kentwood        ,5.17*
Stage Flow Hydrograph=Beaver Creek    ,Kentwood        ,5.13
Stage Flow Hydrograph=Beaver Creek    ,Kentwood        ,5.0975*
Stage Flow Hydrograph=Beaver Creek    ,Kentwood        ,5.065*
Stage Flow Hydrograph=Beaver Creek    ,Kentwood        ,5.0325*
Stage Flow Hydrograph=Beaver Creek    ,Kentwood        ,5.0

--- BeaverSA.u01 (unsteady flow) ---

Flow Title=May 22, 1974 Event
Program Version=3.11
Use Restart= 0
Initial Flow Loc=Beaver Creek    ,Kentwood        ,5.99    ,500
Boundary Location=Beaver Creek    ,Kentwood        ,5.99    ,        ,                ,
Interval=1HOUR
Flow Hydrograph= 100
     500     730 1404.33 2477.03    3875 5502.97    7250 8997.03   1062512022.97
13095.67   13770   14000   1377013095.6712022.97   10625 8997.03    7250 5502.97
    3875 2477.03 1404.33     730     500     400     300     200     200     200
     200     200     200     200     200     200     200     200     200     200
     200     200     200     200     200     200     200     200     200     200
     200     200     200     200     200     200     200     200     200     200
     200     200     200     200     200     200     200     200     200     200
     200     200     200     200     200     200     200     200     200     200
     200     200     200     200     200     200     200     200     200     200
     200     200     200     200     200     200     200     200     200     200
DSS File=C:\HEC\Ras30\Unsteady\beaver.dss
DSS Path=/BEAVER CREEK KENTWOOD/5.99/FLOW/01FEB1999/1HOUR/10 YEAR EVNT/
Use DSS=False
CWMS InputPosition= 0
Use Fixed Start Time=False
Is Critical Boundary=False
Boundary Location=Beaver Creek    ,Kentwood        ,5.0     ,        ,                ,
Rating Curve= 20
  204.14     200  206.09     500  207.26    1000  208.47    2000   209.3    3000
  209.83    4000  210.25    5000  210.68    6000  210.99    7000  211.27    8000
  211.53    9000  211.78   10000  212.02   11000  212.25   12000  212.47   13000
  212.68   14000     213   16000     214   21000     215   26000     216   30000
Use DSS=False
CWMS InputPosition= 0
Use Fixed Start Time=False
Is Critical Boundary=False

--- BeaverSA.g01 (geometry) ---

Geom Title=Beaver Cr. Existing Conditions
Program Version=3.11

River Reach=Beaver Creek    ,Kentwood
Reach XY= 30
 2406173.263075411225841.6254512 2406329.611780611225555.3001116
 2406239.193252211225468.6490219 2406139.356127211225487.4862153
 2406158.193320611225361.2770196 2406273.100200411225349.9747035
 2406342.797815911225240.7189818 2406634.774313611225076.8353993
 2406819.378808911225182.3236823 2406880.197862611225102.5790398
 2406968.732672711225145.9045852 2407040.314021111224907.0322881
  2406863.24439311224684.7533933 2406867.011831911224592.4511404
 2407243.755721411224588.6837015 2407409.523032811224428.5675485
 2407516.895041311224434.2187068 2407256.941757511224268.1229474
 2407283.313829811224108.0067944 2407358.731595111223986.8111909
 2407827.777748111223696.7183894 2407856.033540411223611.9510124
 2407769.382443911223506.4627209 2407881.196585611223357.8240355
 2407815.266403511223092.2195874 2407886.847744111222966.0103816
 2407964.080243211222996.1498934 2408167.174700611222813.6779418
 2408007.0585439 11222595.166481 2408308.4536624 11222306.957399

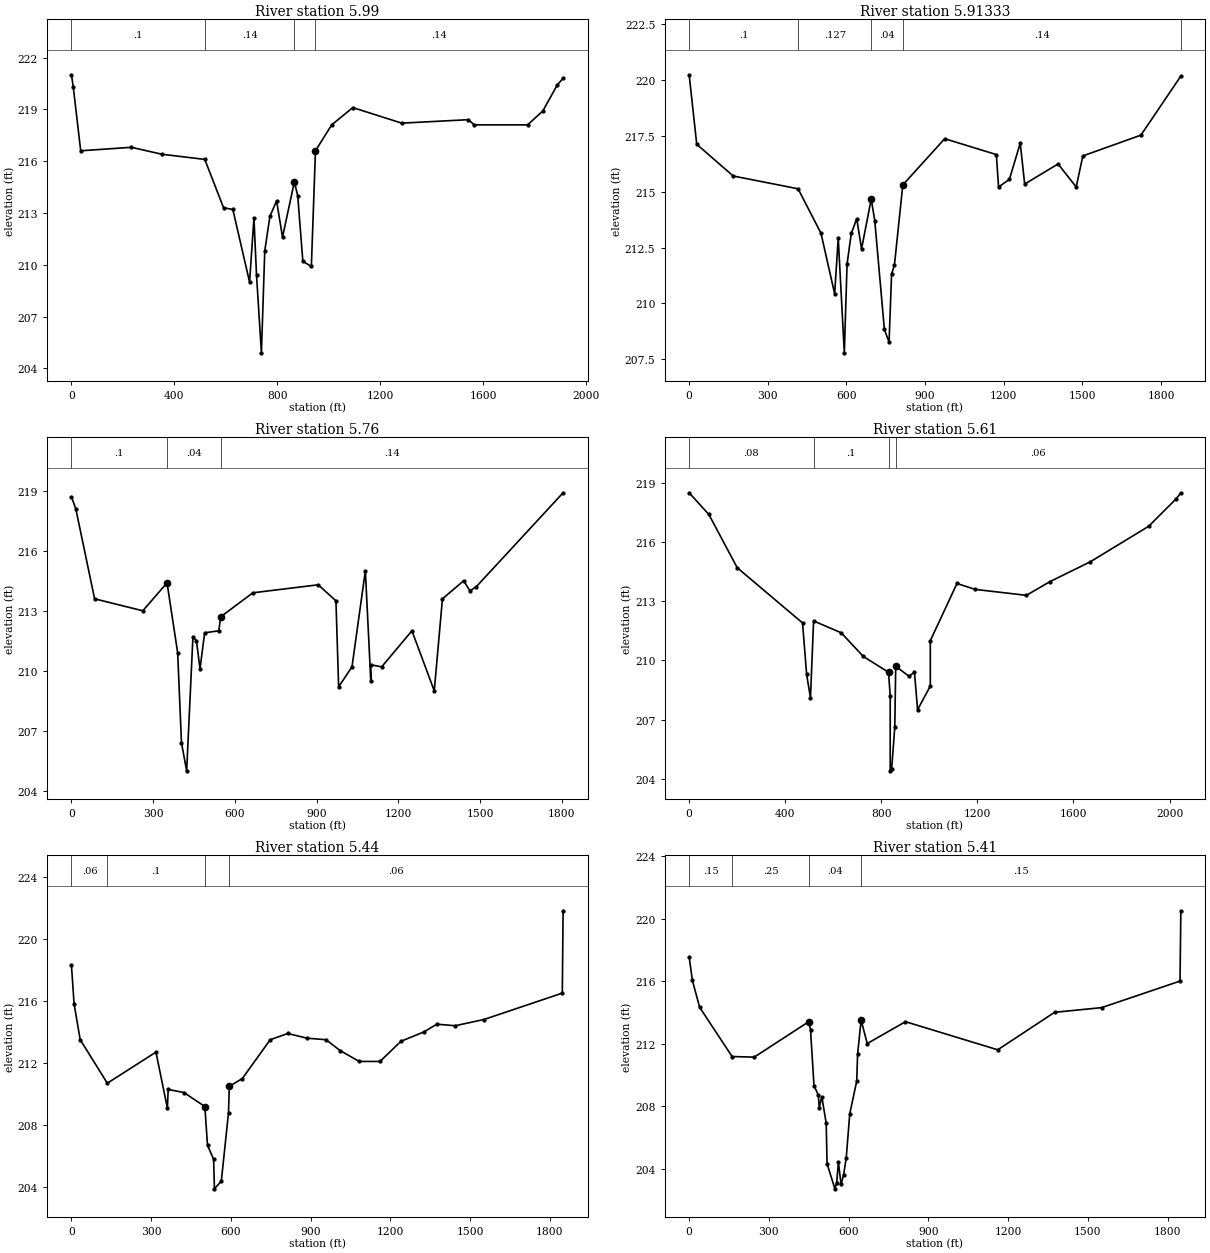
Type RM Length L Ch R = 1 ,5.99    ,146.66,200,133.34
BEGIN DESCRIPTION:
Upstream Boundary Cross Section
END DESCRIPTION:
XS GIS Cut Line= 6
 2407056.580180311226068.4917828 2407028.092692211226061.2288266
 2406707.459746611225979.4826567  2405612.70047411225696.9641347
 2405235.375266111225599.5898876 2405206.909106511225592.2437818
#Sta/Elev= 30
       0     221       7   220.3      36   216.6     233   216.8     351   216.4
     518   216.1     591   213.3     627   213.2     692     209     709   212.7
     719   209.4     738   204.9     751   210.8     771   212.8     797   213.7
     820   211.6     866   214.8     879     214     899   210.2     932   209.9
     948   216.6    1011   218.1    1093   219.1    1283   218.2    1542   218.4
    1565   218.1    1772   218.1    1831   218.9    1887   220.4    1910   220.8
#Mann= 4 , 1 , 0
       0      .1       0     518     .14       0     866     .04       0
     948     .14       0
Bank Sta=866,948
XS Rating Curve= 0
Exp/Cntr=0.3,0.1

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
Type RM Length L Ch R = 1 ,5.91333 ,146.66,200,133.34
XS GIS Cut Line= 6
 2406957.6438998 11225914.886083 2406829.170384111225843.9165183
  2406666.12695811225758.5481469 2406133.112708111225478.0716678
 2405323.167521711225220.6633564 2405295.751775711225211.9503705
#Sta/Elev= 30
       0  220.23   28.86  217.12  168.14   215.7  415.32  215.13  502.71  213.14
  554.83  210.43  568.46  212.93  591.71  207.79  602.13  211.76  618.17  213.13
  639.01  213.79  657.45  212.44  694.33  214.67  707.73  213.71  744.39  208.84
  762.33  208.27  771.96  211.32  782.85  211.72  814.67   215.3  974.49  217.37
 1171.49  216.66 1179.92  215.21 1221.25  215.55 1262.59  217.17 1279.46  215.34
 1406.83  216.24    1476  215.21 1501.31   216.6 1722.89  217.53    1875  220.17
#Mann= 5 , 1 , 0
       0      .1       0  415.32    .127       0  694.33     .04       0
  814.67     .14       0    1875     .14       0
Bank Sta=694.33,814.67
XS Rating Curve= 0
Exp/Cntr=0.3,0.1

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
Type RM Length L Ch R = 1 ,5.76    ,112.5,200,137.5
BEGIN DESCRIPTION:
River Mile 5.76
END DESCRIPTION:
XS GIS Cut Line= 6
 2406759.771338811225607.6746834 2406719.797103511225534.9942556
 2406686.432921911225474.3321074 2406246.6323473 11224800.982262
 2405549.017642611224485.5390912  2405473.43711411224451.3635479
#Sta/Elev= 30
       0   218.7      16   218.1      85   213.6     262     213     351   214.4
     390   210.9     404   206.4     423     205     446   211.7     459   211.5
     472   210.1     489   211.9     541     212     548   212.7     666   213.9
     906   214.3     971   213.5     981   209.2    1030   210.2    1079     215
    1099   209.5    1099   210.3    1139   210.2    1250     212    1332     209
    1362   213.6    1440   214.5    1463     214    1486   214.2    1805   218.9
#Mann= 3 , 1 , 0
       0      .1       0     351     .04       0     548     .14       0
Bank Sta=351,548
XS Rating Curve= 0
Exp/Cntr=0.3,0.1

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
Type RM Length L Ch R = 1 ,5.61    ,96,184,76
BEGIN DESCRIPTION:
River Mile 5.61
END DESCRIPTION:
XS GIS Cut Line= 6
 2407547.416454411225221.4760013 2407507.249076911225174.4546665
 2406902.644556111224466.6835012 2406722.702734411224404.3036697
 2405974.1447562 11224116.396755 2405916.424863811224094.1967964
#Sta/Elev= 28
       0   218.5      82   217.4     200   214.7     472   211.9     489   209.3
     505   208.1     518     212     633   211.4     725   210.2     830   209.4
     837   208.2     837   204.4     843   204.5     856   206.6     860   209.7
     915   209.2     938   209.4     951   207.5    1004   208.7    1004     211
    1115   213.9    1191   213.6    1404   213.3    1503     214    1670     215
    1913   216.8    2028   218.2    2047   218.5
#Mann= 4 , 1 , 0
       0     .08       0     518      .1       0     830     .04       0
     860     .06       0
Bank Sta=830,860
XS Rating Curve= 0
Exp/Cntr=0.3,0.1

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
Type RM Length L Ch R = 1 ,5.44    ,185,135,300
BEGIN DESCRIPTION:
River Mile 5.44
END DESCRIPTION:
XS GIS Cut Line= 3
 2407793.324044311224456.1468925 2407731.797506411224427.3978852
 2406117.267747511223672.9896348
#Sta/Elev= 30
       0   218.3      10   215.8      33   213.5     135   210.7     318   212.7
     361   209.1     364   210.3     423   210.1     502   209.2     512   206.7
     535   205.8     538   203.9     564   204.4     591   208.8     594   210.5
     643     211     748   213.5     814   213.9     886   213.6     958   213.5
    1011   212.8    1083   212.1    1161   212.1    1240   213.4    1326     214
    1375   214.5    1444   214.4    1552   214.8    1847   216.5    1850   221.8
#Mann= 4 , 1 , 0
       0     .06       0     135      .1       0     502     .04       0
     594     .06       0
Bank Sta=502,594
XS Rating Curve= 0
Exp/Cntr=0.5,0.3

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
Type RM Length L Ch R = 1 ,5.41    ,100,100,100
XS GIS Cut Line= 4
 2407861.352030611224396.2915369 2407788.568372911224362.3630029
 2406257.3688531 11223648.585258 2406184.5851955 11223614.656724
#Sta/Elev= 30
       0  217.55      12  216.05    39.5  214.32   161.5  211.17   244.8  211.13
     450   213.4   456.6   212.9   469.7   209.3   486.1   208.7   489.4   207.9
   499.2   208.6   515.6   206.9   518.9   204.3   548.4   202.7     555   203.1
   561.6   204.4   571.4     203   581.2   203.6   591.1   204.7   604.2   207.5
   630.5   209.6   633.7   211.3     647   213.5     670     212     814   213.4
    1161   211.6    1375     214    1552   214.3    1847     216    1850   220.5
#Mann= 4 ,-1 , 0
       0     .15       0   161.5     .25       0     450     .04       0
     647     .15       0
Bank Sta=450,647
XS Rating Curve= 0
Exp/Cntr=0.3,0.1

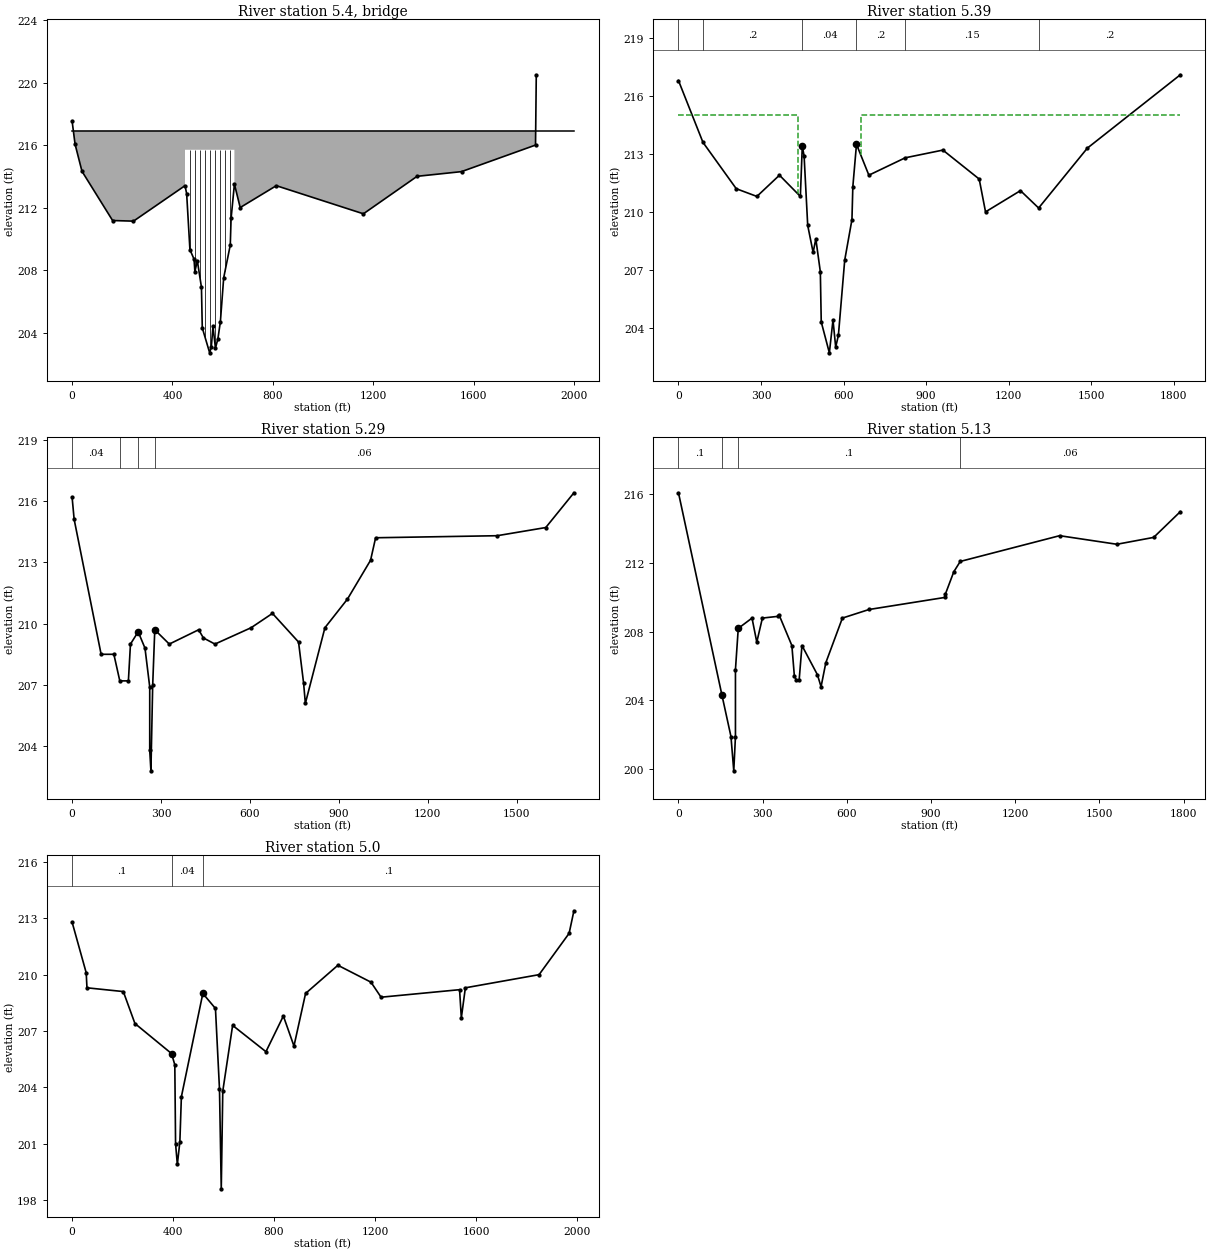
Type RM Length L Ch R = 3 ,5.4     ,,,
Bridge Culvert--1,0,0,-1, 0
Deck Dist Width WeirC Skew NumUp NumDn MinLoCord MaxHiCord MaxSubmerge Is_Ogee
30,40,2.6,0, 6, 6, , , 0.95, 0, 0,0,,
       0     450     450     647     647    2000
  216.93  216.93  216.93  216.93  216.93  216.93
     200     200   215.7   215.7     200     200
       0     450     450     647     647    2000
  216.93  216.93  216.93  216.93  216.93  216.93
     200     200   215.7   215.7     200     200
Pier Skew, UpSta & Num, DnSta & Num=  ,470, 2 ,470, 2 , 0 , 0 , 0 ,,
    1.25    1.25
   202.7   215.7
    1.25    1.25
   202.7   215.7
Pier Skew, UpSta & Num, DnSta & Num=  ,490, 2 ,490, 2 , 0 , 0 , 0 ,,
    1.25    1.25
   202.7   215.7
    1.25    1.25
   202.7   215.7
Pier Skew, UpSta & Num, DnSta & Num=  ,510, 2 ,510, 2 , 0 , 0 , 0 ,,
    1.25    1.25
   202.7   215.7
    1.25    1.25
   202.7   215.7
Pier Skew, UpSta & Num, DnSta & Num=  ,530, 2 ,530, 2 , 0 , 0 , 0 ,,
    1.25    1.25
   202.7   215.7
    1.25    1.25
   202.7   215.7
Pier Skew, UpSta & Num, DnSta & Num=  ,550, 2 ,550, 2 , 0 , 0 , 0 ,,
    1.25    1.25
   202.7   215.7
    1.25    1.25
   202.7   215.7
Pier Skew, UpSta & Num, DnSta & Num=  ,570, 2 ,570, 2 , 0 , 0 , 0 ,,
    1.25    1.25
   202.7   215.7
    1.25    1.25
   202.7   215.7
Pier Skew, UpSta & Num, DnSta & Num=  ,590, 2 ,590, 2 , 0 , 0 , 0 ,,
    1.25    1.25
   202.7   215.7
    1.25    1.25
   202.7   215.7
Pier Skew, UpSta & Num, DnSta & Num=  ,610, 2 ,610, 2 , 0 , 0 , 0 ,,
    1.25    1.25
   202.7   215.7
    1.25    1.25
   202.7   215.7
Pier Skew, UpSta & Num, DnSta & Num=  ,630, 2 ,630, 2 , 0 , 0 , 0 ,,
    1.25    1.25
   202.7   215.7
    1.25    1.25
   202.7   215.7
BR Coef=-1 , 0 , 0 ,, 0 ,,,0.8,0,,1,
WSPro=,,,, 1 ,,,, 0 ,,,, 0 ,,,,-1 ,-1 ,-1 , 0 , 0 , 0 , 0 , 0
BC Design=,, 0 ,, 0 ,,9,470,470,20,1.25
BC HTab HWMax=225
BC HTab TWMax=220
BC HTab MaxSwellHead=5
BC HTab MaxFlow=50000

Type RM Length L Ch R = 1 ,5.39    ,106.67,166.67,193.33
BEGIN DESCRIPTION:
Downstream of bridge embankment
END DESCRIPTION:
XS GIS Cut Line= 4
 2407932.559564711224255.4473804 2407886.635625211224233.2724826
 2406335.943420811223484.5030724 2406290.019481311223462.3281747
#Sta/Elev= 30
       0   216.8      89   213.6     210   211.2     285   210.8     367   211.9
     443   210.8     450   213.4   456.6   212.9   469.7   209.3   489.4   207.9
   499.2   208.6   515.6   206.9   518.9   204.3   548.4   202.7   561.6   204.4
   571.4     203   581.2   203.6   604.2   207.5   630.5   209.6   633.7   211.3
     647   213.5     692   211.9     824   212.8     961   213.2    1093   211.7
    1116     210    1243   211.1    1309   210.2    1486   213.3    1824   217.1
#Mann= 6 , 1 , 0
       0     .15       0      89      .2       0     450     .04       0
     647      .2       0     824     .15       0    1309      .2       0
#XS Ineff= 2 , 0
       0     435     215     662       0     215
Permanent Ineff=
       F       F
Bank Sta=450,647
XS Rating Curve= 0
Exp/Cntr=0.5,0.3

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
Type RM Length L Ch R = 1 ,5.29    ,205,208.25,205
BEGIN DESCRIPTION:
River Mile 5.29
END DESCRIPTION:
XS GIS Cut Line= 2
 2408033.818880111223569.7075669 2406507.823460611222836.5043348
#Sta/Elev= 30
       0   216.2       7   215.1      98   208.5     141   208.5     161   207.2
     190   207.2     197     209     223   209.6     246   208.8     262   206.9
     262   203.8     266   202.8     272     207     279   209.7     328     209
     427   209.7     443   209.3     482     209     604   209.8     676   210.5
     764   209.1     781   207.1     787   206.1     853   209.8     929   211.2
    1007   213.1    1024   214.2    1434   214.3    1598   214.7    1693   216.4
#Mann= 4 , 1 , 0
       0     .04       0     161     .06       0     223     .04       0
     279     .06       0
Bank Sta=223,279
XS Rating Curve= 0
Exp/Cntr=0.3,0.1

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
Type RM Length L Ch R = 1 ,5.13    ,155,177.5,170
BEGIN DESCRIPTION:
River Mile 5.13
END DESCRIPTION:
XS GIS Cut Line= 4
 2408155.106505211223077.0821163 2408141.207585411223066.6526772
 2406738.864725811222014.3659081 2406724.9658059 11222003.936469
#Sta/Elev= 30
       0   216.1     155   204.3     187   201.9     197   199.9     203   201.9
     203   205.8     213   208.2     262   208.8     279   207.4     299   208.8
     354   208.9     358     209     404   207.2     413   205.4     420   205.2
     430   205.2     440   207.2     495   205.5     508   204.8     525   206.2
     584   208.8     679   209.3     948     210     951   210.2     981   211.5
    1004   212.1    1358   213.6    1562   213.1    1693   213.5    1788     215
#Mann= 4 , 1 , 0
       0      .1       0     155     .04       0     213      .1       0
    1004     .06       0
Bank Sta=155,213
XS Rating Curve= 0
Exp/Cntr=0.3,0.1

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
Type RM Length L Ch R = 1 ,5.0     ,0,0,0
BEGIN DESCRIPTION:
Downstream Boundary Cross Section
END DESCRIPTION:
XS GIS Cut Line= 2
 2408609.056321811222696.1394271 2407044.866399411221466.7351757
#Sta/Elev= 30
       0   212.8      56   210.1      59   209.3     203   209.1     249   207.4
     394   205.8     407   205.2     410     201     417   199.9     427   201.1
     433   203.5     518     209     568   208.2     584   203.9     591   198.6
     597   203.8     636   207.3     768   205.9     837   207.8     879   206.2
     925     209    1053   210.5    1184   209.6    1224   208.8    1535   209.2
    1542   207.7    1558   209.3    1850     210    1969   212.2    1988   213.4
#Mann= 3 , 0 , 0
       0      .1       0     394     .04       0     518      .1       0
Bank Sta=394,518
XS Rating Curve= 0
Exp/Cntr=0.3,0.1
Stream Node=Beaver Creek    ,Kentwood        , 0 , 0 ,Upstream end
Stream Node=Beaver Creek    ,Kentwood        , 0 , 1 ,Downstream end

Chan Stop Cuts=-1